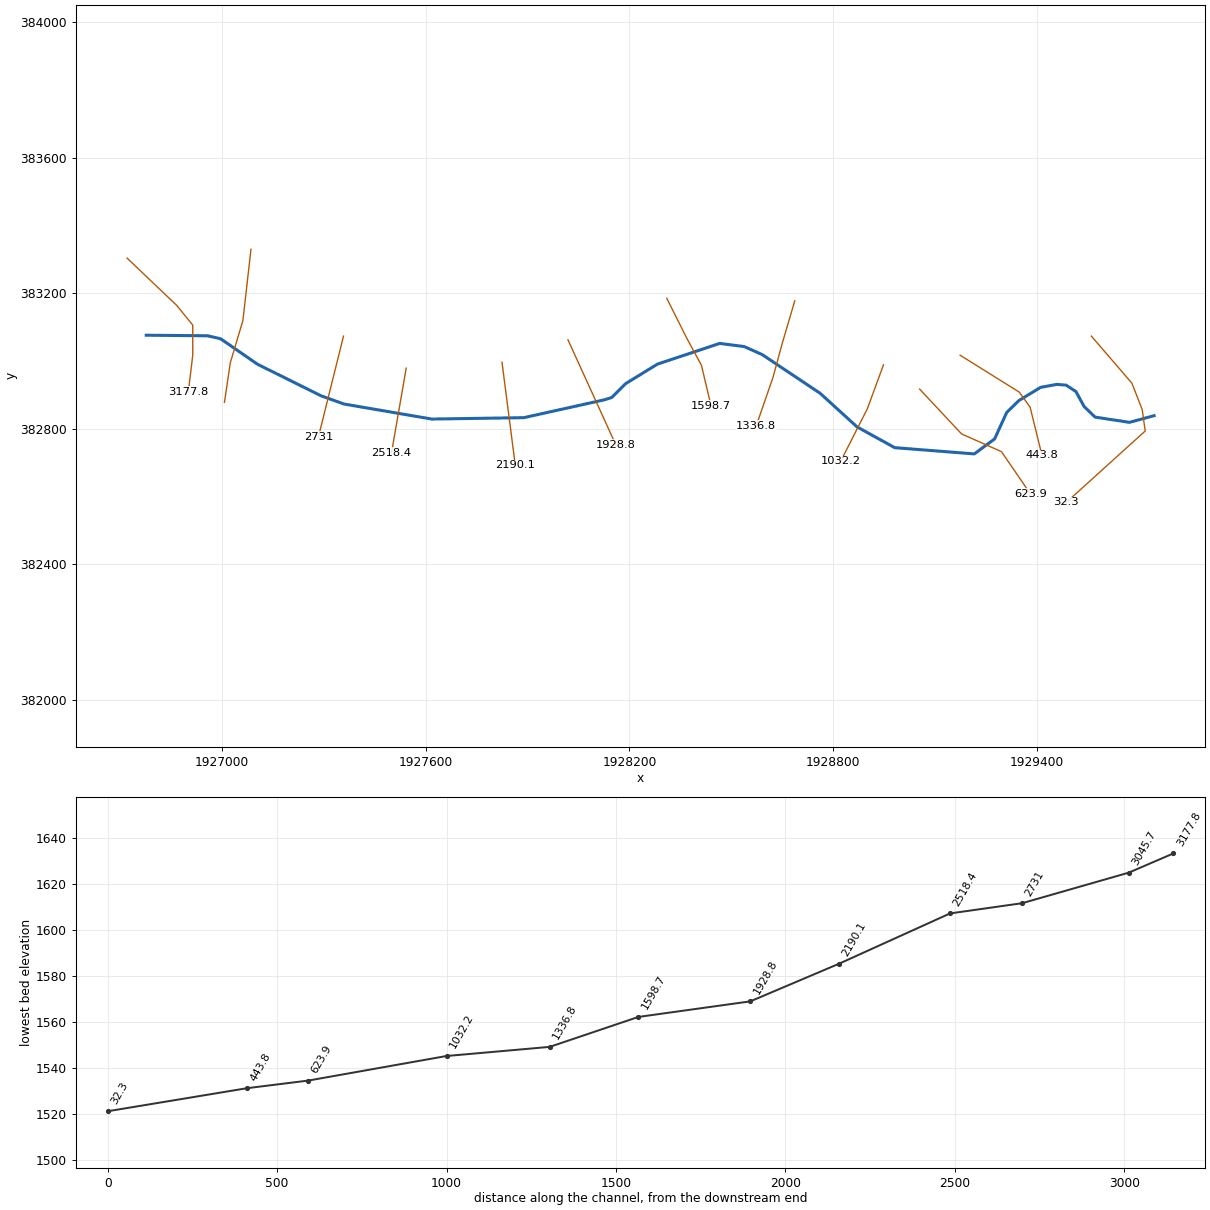
--- MARTINCK.prj (project) ---

Proj Title=MARTINCK
Current Plan=p01
Geom File=g01
Flow File=f01
Plan File=p01
DSS Export Rating Curves=0
DSS Export Rating Curve Sorted=0
DSS Export Volume Flow Curves=0
DXF OffsetX=0
DXF OffsetY=0
DXF ScaleX=0
DXF ScaleY=0

--- MARTINCK.p01 (plan) ---

Plan Title=Floodplain
Program Version=4.00
Geom File=g01
Flow File=f01
K Sum by GR=0
Std Step Tol=0.01
Critical Tol=0.01
Num of Std Step Trials=20
Max Error Tol=0.3
Flow Tol Ratio=0.001
Split Flow NTrial=30
Split Flow Tol=0.02
Split Flow Ratio=0.02
Log Output Level=0
Friction Slope Method=1
Unsteady Friction Slope Method=2
Unsteady Bridges Friction Slope Method=1
Global Log Level=0
CheckData=False
Run HTab=0
Run UNet=0
Run PostProcess=0
UNET Theta=0
UNET Theta Warmup=0
UNET ZTol=0
UNET ZSATol=0
UNET MxIter=0
UNET MaxInSteps=0
UNET DtIC=0
UNET DtMin=0
UNET MaxCRTS=0
UNET WFStab=0
UNET SFStab=0
UNET WFX=0
UNET SFX=0
UNET DSS MLevel=0
UNET DZMax Abort=0
UNET Convert EG Bridges=0
UNET Use Existing IB Tables=0
UNET Froude Limit=0
UNET Froude Power=0
Write IC File=0
Echo Input=False
Echo Output=False
Write Detailed=0

--- MARTINCK.f01 (steady flow) ---

Flow Title=NFF Regression Equation
Program Version=4.00
Number of Profiles=1
Profile Names=P100yr
River Rch & RM=MARTINCK,Main      ,3177.8
  383.28
River Rch & RM=MARTINCK,Main      ,3045.7
1111.414
River Rch & RM=MARTINCK,Main      ,32.3
1151.166
Boundary for River Rch & Prof#=MARTINCK,Main      ,1
Up Type=0
Dn Type=3
Dn Slope=0.022959

--- MARTINCK.g01 (geometry) ---

Geom Title=USGS 10m DEM
Program Version=4.00

River Reach=MARTINCK     ,Main
Reach XY= 30
     1926777.566      383076.114     1926958.121      383074.378
     1926996.316      383065.698     1927104.880      382990.613
     1927292.033      382897.411     1927359.742      382873.105
     1927618.017      382828.769     1927889.117      382832.889
     1928125.801      382885.475     1928147.746      382892.285
     1928188.735      382933.218     1928282.335      382990.798
     1928465.878      383051.979     1928538.212      383042.481
     1928590.917      383018.881     1928761.585      382904.589
     1928869.845      382805.752     1928980.836      382744.416
     1929215.211      382725.970     1929274.949      382770.176
     1929310.697      382848.583     1929346.504      382883.305
     1929410.523      382922.367     1929458.266      382931.048
     1929485.393      382928.878     1929514.251      382909.970
     1929538.583      382865.655     1929570.709      382834.521
     1929671.824      382819.069     1929744.386      382838.736

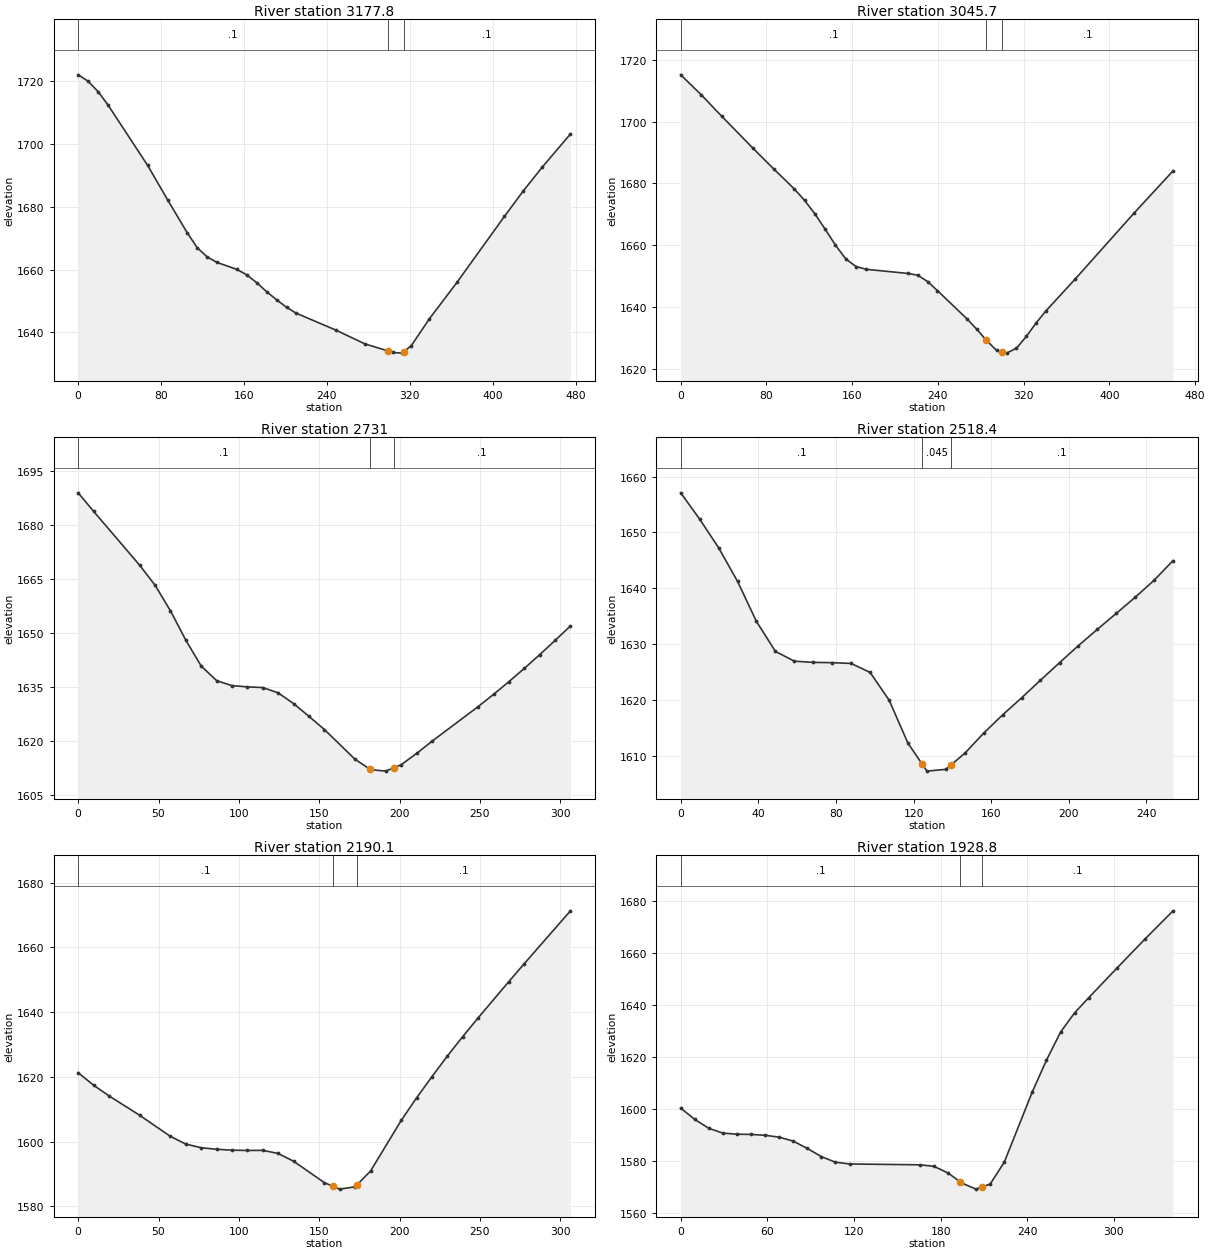
Type RM Length L Ch R = 1 ,3177.8,138.1,132.1,125.8
XS GIS Cut Line= 5
     1926721.287      383303.444     1926866.686      383164.555
     1926914.429      383105.961     1926914.429      383016.985
     1926901.408      382908.478
#Sta/Elev= 30
       0 1722.01     9.6 1719.99    19.2 1716.67    28.7 1712.46    67.0 1693.18
    86.2 1682.25   105.3 1671.66   114.9 1666.94   124.5 1664.00   134.0 1662.26
   153.2 1660.04   162.8 1658.27   172.4 1655.78   181.9 1652.93   191.5 1650.35
   201.1 1647.97   210.5 1646.07   248.3 1640.76   276.7 1636.31   299.1 1634.06
   303.4 1633.59   312.2 1633.38   314.1 1633.87   321.2 1635.68   338.9 1644.35
   365.6 1655.99   411.2 1676.92   429.4 1685.03   447.6 1692.57   474.9 1703.17
#Mann= 3 , 0 , 0
       0     0.1       0   299.1   0.045       0   314.1     0.1       0
Bank Sta=299.1,314.1
Exp/Cntr=0.3,0.1

Type RM Length L Ch R = 1 ,3045.7,314.1,314.7,315.4
XS GIS Cut Line= 4
     1927085.870      383329.485     1927061.999      383118.982
     1927025.106      382995.284     1927007.745      382878.096
#Sta/Elev= 30
       0 1715.23    19.3 1708.70    38.5 1701.72    67.4 1691.44    86.7 1684.75
   105.9 1678.26   115.6 1674.52   125.2 1670.14   134.8 1665.18   144.4 1660.00
   154.1 1655.51   163.7 1653.05   173.3 1652.17   211.8 1650.84   221.1 1650.27
   230.3 1648.22   239.5 1645.29   267.2 1636.08   276.4 1632.70     285 1629.23
   294.8 1625.86     300 1625.37   304.0 1625.00   313.3 1626.59   322.5 1630.41
   331.7 1634.81   340.9 1638.73   368.3 1649.09   423.0 1670.39   459.4 1684.08
#Mann= 3 , 0 , 0
       0     0.1       0     285   0.045       0     300     0.1       0
Bank Sta=285,300
Exp/Cntr=0.3,0.1

Type RM Length L Ch R = 1 ,2731,210.9,212.6,214.1
XS GIS Cut Line= 2
     1927358.223      383073.409     1927284.438      382776.100
#Sta/Elev= 30
       0 1689.05     9.6 1683.91    38.3 1668.93    47.9 1663.34    57.4 1656.29
    67.0 1648.10    76.6 1640.89    86.2 1636.85    95.7 1635.48   105.3 1635.13
   114.9 1634.94   124.4 1633.48   134.0 1630.50   143.6 1626.94   153.2 1623.28
   172.3 1615.00   181.5 1612.26   181.9 1612.14   191.4 1611.72   196.5 1612.67
   201.0 1613.50   210.6 1616.64   220.2 1620.03   248.9 1629.66   258.5 1633.06
   268.0 1636.58   277.6 1640.26   287.2 1644.10   296.8 1648.05   306.3 1652.08
#Mann= 3 , 0 , 0
       0     0.1       0   181.5   0.045       0   196.5     0.1       0
Bank Sta=181.5,196.5
Exp/Cntr=0.3,0.1

Type RM Length L Ch R = 1 ,2518.4,321.4,328.3,335
XS GIS Cut Line= 2
     1927542.829      382978.791     1927499.426      382728.791
#Sta/Elev= 29
       0 1657.08     9.8 1652.35    19.5 1647.26    29.3 1641.22    39.0 1634.08
    48.8 1628.70    58.6 1626.95    68.3 1626.74    78.1 1626.69    87.8 1626.55
    97.6 1624.94   107.4 1619.98   117.1 1612.28   124.5 1608.50   126.9 1607.28
   136.6 1607.60   139.5 1608.45   146.4 1610.48   156.2 1614.11   165.9 1617.35
   175.7 1620.41   185.4 1623.55   195.2 1626.68   204.9 1629.72   214.7 1632.65
   224.5 1635.52   234.2 1638.39   244.0 1641.45   253.7 1644.95
#Mann= 3 , 0 , 0
       0     0.1       0   124.5   0.045       0   139.5     0.1       0
Bank Sta=124.5,139.5
Exp/Cntr=0.3,0.1

Type RM Length L Ch R = 1 ,2190.1,254.4,261.4,268
XS GIS Cut Line= 2
     1927824.803      382996.369     1927863.865      382692.550
#Sta/Elev= 28
       0 1621.31     9.6 1617.46    19.2 1614.15    38.3 1608.16    57.4 1601.65
    67.0 1599.27    76.6 1598.14    86.2 1597.66    95.7 1597.39   105.3 1597.30
   114.9 1597.33   124.4 1596.38   134.0 1593.99   153.2 1587.36   158.5 1586.24
   162.7 1585.36   172.3 1586.07   173.5 1586.68   181.9 1590.94   201.0 1606.56
   210.6 1613.58   220.2 1620.13   229.7 1626.45   239.3 1632.47   248.9 1638.26
   268.0 1649.47   277.6 1655.00   306.3 1671.30
#Mann= 3 , 0 , 0
       0     0.1       0   158.5   0.045       0   173.5     0.1       0
Bank Sta=158.5,173.5
Exp/Cntr=0.3,0.1

Type RM Length L Ch R = 1 ,1928.8,328.4,330.1,331.7
XS GIS Cut Line= 2
     1928019.030      383062.558     1928160.089      382752.228
#Sta/Elev= 30
       0 1600.24     9.7 1595.89    19.5 1592.46    29.2 1590.60    39.0 1590.20
    48.7 1590.10    58.4 1589.78    68.2 1589.05    77.9 1587.53    87.7 1584.70
    97.4 1581.55   107.1 1579.40   116.9 1578.73   165.6 1578.40   175.3 1577.82
   185.0 1575.28   193.5 1571.85   194.8 1571.32   204.5 1569.03   208.5 1569.83
   214.3 1570.99   224.0 1579.37   243.5 1606.56   253.2 1618.64   263.0 1629.50
   272.7 1636.92   282.4 1642.71   301.9 1654.09   321.4 1665.33   340.9 1676.25
#Mann= 3 , 0 , 0
       0     0.1       0   193.5   0.045       0   208.5     0.1       0
Bank Sta=193.5,208.5
Exp/Cntr=0.3,0.1

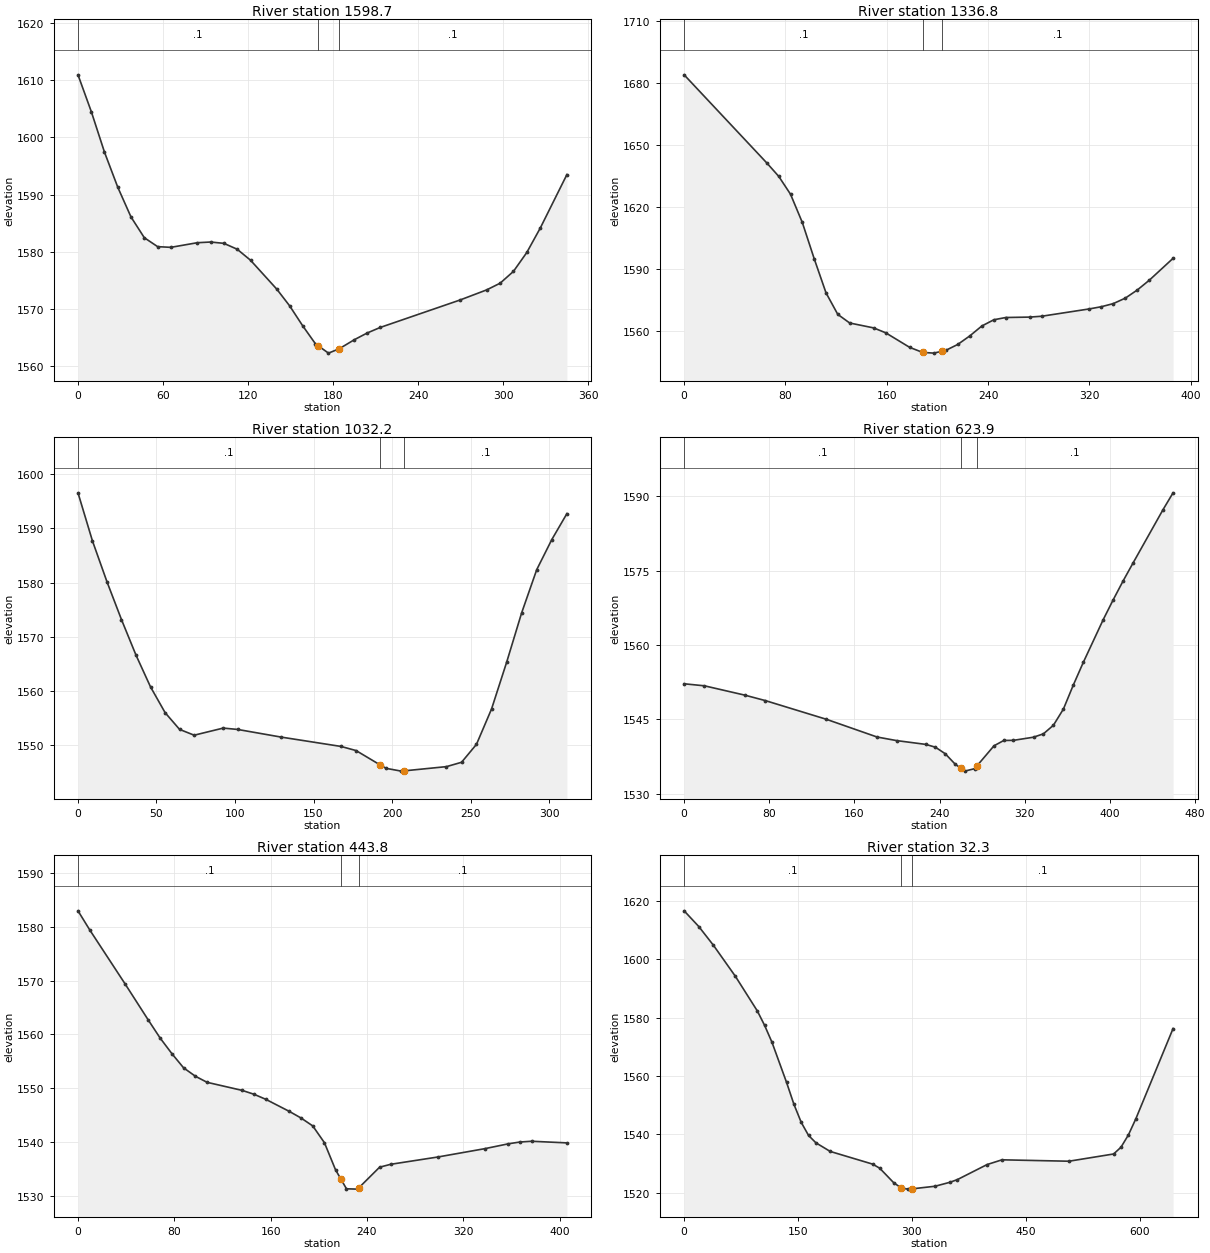
Type RM Length L Ch R = 1 ,1598.7,278.6,261.9,244.6
XS GIS Cut Line= 4
     1928309.829      383185.171     1928368.422      383067.984
     1928411.825      382987.688     1928440.037      382868.331
#Sta/Elev= 30
       0 1610.94     9.4 1604.50    18.7 1597.41    28.1 1591.26    37.4 1586.08
    46.8 1582.45    56.2 1580.89    65.5 1580.77    84.2 1581.58    93.6 1581.70
   102.9 1581.47   112.3 1580.44   121.7 1578.52   140.2 1573.47   149.3 1570.54
   158.4 1567.09   167.5 1563.90   169.2 1563.60   176.7 1562.27   184.2 1563.02
   194.9 1564.61   204.0 1565.79   213.2 1566.76   269.5 1571.56   288.3 1573.33
   297.8 1574.50   307.2 1576.57   316.6 1579.87   326.1 1584.14   344.9 1593.50
#Mann= 3 , 0 , 0
       0     0.1       0   169.2   0.045       0   184.2     0.1       0
Bank Sta=169.2,184.2
Exp/Cntr=0.3,0.1

Type RM Length L Ch R = 1 ,1336.8,309.3,304.6,299.5
XS GIS Cut Line= 4
     1928686.699      383177.512     1928649.829      383052.163
     1928622.458      382951.446     1928573.149      382808.715
#Sta/Elev= 30
       0 1684.13    65.3 1641.39    74.7 1634.91    84.0 1626.24    93.3 1612.56
   102.7 1594.96   112.0 1578.47   121.3 1568.02   130.7 1563.84   149.6 1561.47
   159.1 1559.10   178.1 1552.02   188.2 1549.61   197.1 1549.24   203.2 1550.11
   206.6 1550.59   216.0 1553.44   225.5 1557.58   235.0 1562.38   244.5 1565.41
   253.9 1566.50   272.8 1566.71   282.2 1567.11   320.0 1570.68   329.4 1571.74
   338.8 1573.24   348.3 1575.90   357.7 1579.81   367.2 1584.56   386.0 1595.19
#Mann= 3 , 0 , 0
       0     0.1       0   188.2   0.045       0   203.2     0.1       0
Bank Sta=188.2,203.2
Exp/Cntr=0.3,0.1

Type RM Length L Ch R = 1 ,1032.2,369.2,408.3,445.9
XS GIS Cut Line= 3
     1928947.849      382988.774     1928900.106      382858.565
     1928821.981      382704.485
#Sta/Elev= 27
       0 1596.55     9.2 1587.70    18.5 1580.13    27.7 1573.19    37.0 1566.61
    46.2 1560.79    55.5 1556.04    64.7 1552.96    74.0 1551.89    92.5 1553.20
   101.7 1552.95   129.4 1551.54   167.5 1549.82   177.1 1549.06   192.4 1546.42
   196.3 1545.78   205.9 1545.27   207.4 1545.31   234.7 1546.10   244.3 1546.90
   253.8 1550.21   263.4 1556.72   273.0 1565.32   282.6 1574.46   292.2 1582.41
   301.8 1587.95   311.4 1592.72
#Mann= 3 , 0 , 0
       0     0.1       0   192.4   0.045       0   207.4     0.1       0
Bank Sta=192.4,207.4
Exp/Cntr=0.3,0.1

Type RM Length L Ch R = 1 ,623.9,193.2,180.1,167.4
XS GIS Cut Line= 4
     1929054.186      382917.159     1929177.884      382784.780
     1929295.072      382732.697     1929379.707      382608.999
#Sta/Elev= 30
       0 1552.19    19.1 1551.78    57.2 1549.89    76.3 1548.80   133.5 1545.04
   181.2 1541.46   199.5 1540.74   227.0 1539.97   236.1 1539.40   245.3 1538.08
   254.5 1536.01   259.7 1535.19   263.6 1534.58   272.8 1535.07   274.7 1535.55
   291.1 1539.69   300.3 1540.76   309.4 1540.79   328.2 1541.42   337.5 1542.10
   346.9 1543.83   356.3 1547.10   365.6 1551.94   375.0 1556.52   393.7 1565.13
   403.1 1569.14   412.5 1572.98   421.8 1576.58   449.9 1587.31   459.3 1590.69
#Mann= 3 , 0 , 0
       0     0.1       0   259.7   0.045       0   274.7     0.1       0
Bank Sta=259.7,274.7
Exp/Cntr=0.3,0.1

Type RM Length L Ch R = 1 ,443.8,422.8,411.5,400.1
XS GIS Cut Line= 4
     1929173.544      383016.985     1929347.155      382908.478
     1929379.418      382863.991     1929414.429      382721.846
#Sta/Elev= 29
       0 1582.97     9.8 1579.41    39.0 1569.44    58.5 1562.65    68.2 1559.35
    78.0 1556.44    87.7 1553.81    97.5 1552.25   107.2 1551.12   136.5 1549.61
   146.2 1548.90   156.0 1547.96   175.5 1545.72   185.2 1544.50   195.0 1543.02
   204.7 1539.90   213.9 1534.88   218.2 1533.21   223.0 1531.34   232.2 1531.28
   233.2 1531.51   250.5 1535.35   259.7 1535.89   298.7 1537.24   337.8 1538.79
   357.3 1539.69   367.0 1540.03   376.8 1540.17   406.1 1539.87
#Mann= 3 , 0 , 0
       0     0.1       0   218.2   0.045       0   233.2     0.1       0
Bank Sta=218.2,233.2
Exp/Cntr=0.3,0.1

Type RM Length L Ch R = 1 ,32.3,29.5,32.3,35.2
XS GIS Cut Line= 5
     1929559.829      383073.409     1929679.186      382934.520
     1929709.568      382856.395     1929718.249      382793.461
     1929486.044      382582.958
#Sta/Elev= 30
       0 1616.58    19.3 1611.20    38.6 1604.77    67.5 1594.15    96.4 1582.28
   106.0 1577.33   115.7 1571.54   134.9 1557.80   144.6 1550.30   154.2 1544.12
   163.8 1539.66   173.5 1537.12   192.4 1534.16   248.3 1529.81   257.6 1528.41
   276.0 1523.44   285.6 1521.72   294.2 1521.25   300.6 1521.36   330.5 1522.24
   350.1 1523.60   359.9 1524.52   399.0 1529.67   418.6 1531.29   506.8 1530.81
   565.6 1533.29   575.3 1535.60   585.1 1539.82   594.9 1545.36   643.9 1576.26
#Mann= 3 , 0 , 0
       0     0.1       0   285.6   0.045       0   300.6     0.1       0
Bank Sta=285.6,300.6
Exp/Cntr=0.3,0.1